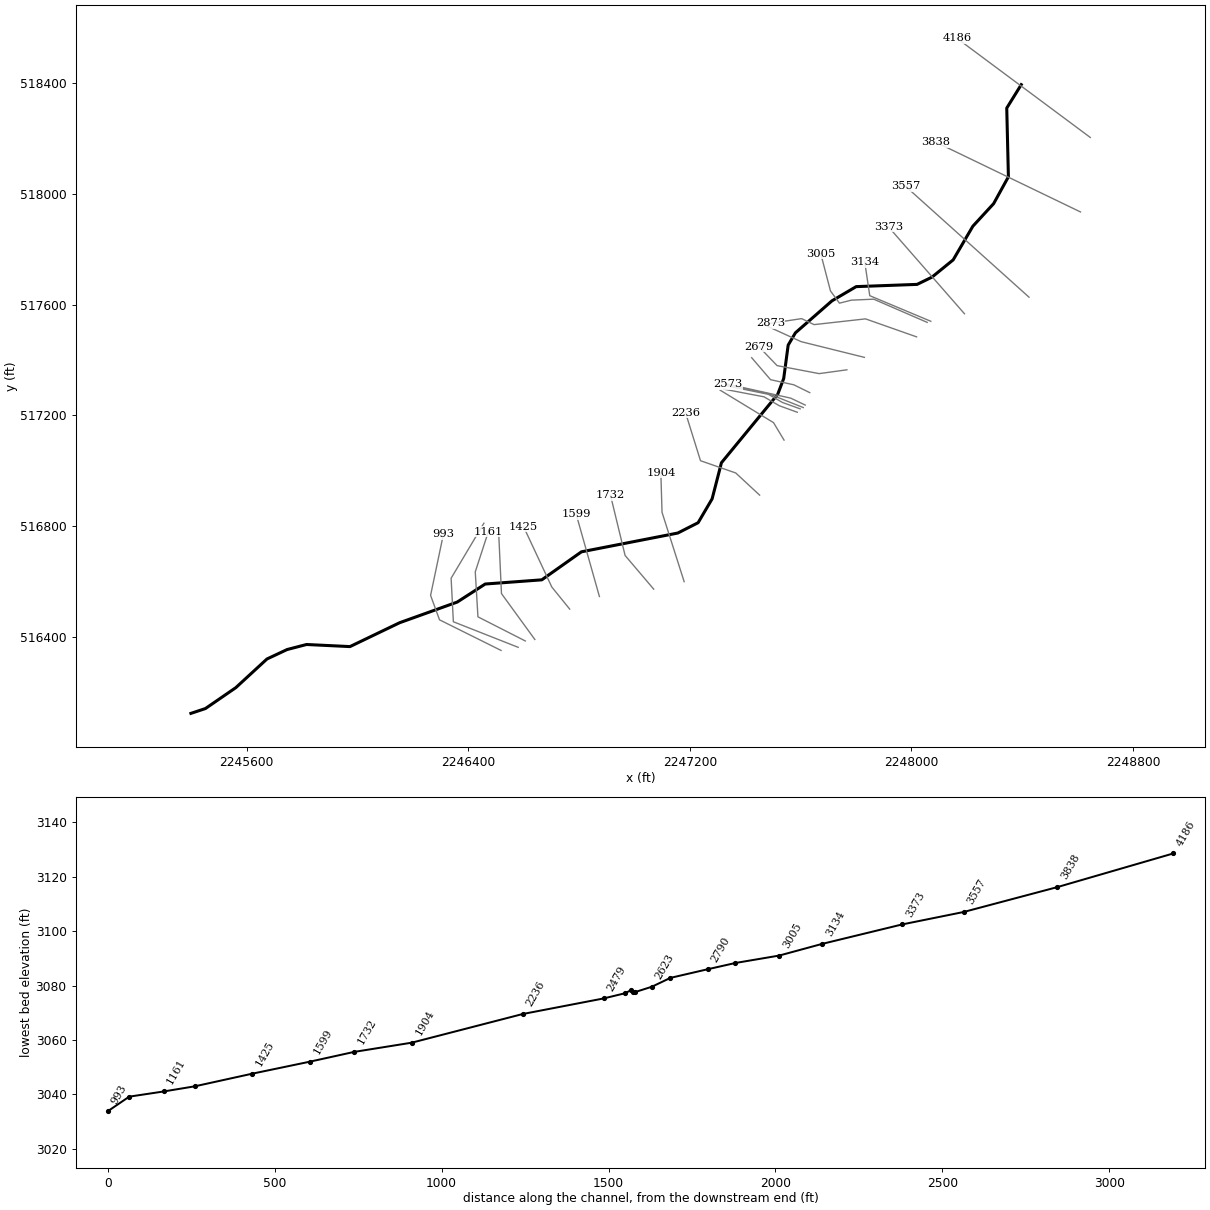
--- CUPRN.prj (project) ---

Proj Title=CUPRN
Current Plan=p01
Default Exp/Contr=0,0
English Units
Geom File=g01
Flow File=f01
Plan File=p01
Background Map Layer=QC
Background Map Layer=Inundation Boundary (01pct Value_0)
BEGIN DESCRIPTION:
----------MODEL BY WOOD PLC 2021----------
Stream Name: Cup Run
Flood Zone: Enhanced Approximate
Pocahontas County, WV
HEC-RAS Version: RAS 6.1
Vertical Datum: NAVD88
Projection: NAD 1983 StatePlane West Virginia S FIPS 4702 (US Feet)
Terrain: 1-meter LIDAR (FEMA Region III 3DEP collected 2016-2018)
Land Use: 2019 NLCD
Hydrologic Method:
WV SIR2010-5033 regression equations
Model Notes:
Normal Depth tie in to Big Spring Fork
END DESCRIPTION:
DSS Export Rating Curves= 0
DSS Export Rating Curve Sorted= 0
DSS Export Volume Flow Curves= 0
DXF OffsetX= 0
DXF OffsetY= 0
DXF ScaleX= 0
DXF ScaleY= 0

--- CUPRN.p01 (plan) ---

Plan Title=Floodplain
Program Version=6.00
Short Identifier=Floodplain
Geom File=g01
Flow File=f01
Subcritical Flow
K Sum by GR= 0
Std Step Tol= 0.01
Critical Tol= 0.01
Num of Std Step Trials= 20
Max Error Tol= 0.3
Flow Tol Ratio= 0.001
Split Flow NTrial= 30
Split Flow Tol= 0.02
Split Flow Ratio= 0.02
Log Output Level= 0
Friction Slope Method= 1
Unsteady Friction Slope Method= 2
Unsteady Bridges Friction Slope Method= 1
Parabolic Critical Depth
Global Vel Dist= 0 , 0 , 0
Global Log Level= 0
CheckData=False
Encroach Param=-1 ,0,0, 0
Mapping Interval=1HOUR
Computation Time Step Use Courant=        0
Computation Time Step Use Time Series=    0
Computation Time Step Count To Double=0
Computation Time Step Max Doubling=0
Computation Time Step Max Halving=0
Computation Time Step Residence Courant=0
Run HTab= 0
Run UNet= 0
Run Sediment= 0
Run PostProcess= 0
Run WQNet= 0
Run RASMapper=-1
UNET Theta= 0
UNET Theta Warmup= 0
UNET ZTol= 0
UNET ZSATol= 0
UNET MxIter= 0
UNET Max Iter WO Improvement= 0
UNET MaxInSteps= 0
UNET DtIC= 0
UNET DtMin= 0
UNET MaxCRTS= 0
UNET WFStab= 0
UNET SFStab= 0
UNET WFX= 1
UNET SFX= 1
UNET Gravity=32.174
UNET 1D Methodology=Finite Difference
UNET DSS MLevel= 1
UNET Pardiso=0
UNET DZMax Abort= 0
UNET Use Existing IB Tables= 0
UNET Froude Reduction=False
UNET Froude Limit= 0
UNET Froude Power= 0
UNET D1 Cores= 0
UNET WindReference=Eulerian
UNET WindDragFormulation=Hsu (1988)
UNET D2 Coriolis=0
UNET D2 Cores= 0
UNET D2 Theta= 1
UNET D2 Theta Warmup= 1
UNET D2 Z Tol= 0.01
UNET D2 Volume Tol= 0.01
UNET D2 Max Iterations= 20
UNET D2 Equation= 0
UNET D2 RampUpFraction=0.1
UNET D2 TimeSlices= 1
UNET D2 Turbulence Formulation=Non-Conservative (original)
UNET D2 Eddy Viscosity=0.3
UNET D2 Transverse Eddy Viscosity=0.1
UNET D2 Smagorinsky Mixing=0
UNET D2 BCVolumeCheck=0
UNET D2 Cores=0
UNET D2 SolverType=PARDISO (Direct)
UNET D2 Minimum Iterations= 2147483647
UNET D2 Maximum Iterations= 2147483647
UNET D2 Restart Number= 10
UNET D2 Relaxation Coeff=1.3
UNET D2 SOR Precondition Iterations= 10
UNET D2 ILUT Maximum Fill= 8
UNET D2 ILUT Tolerance=1E-08
UNET D1D2 MaxIter= 0
UNET D1D2 ZTol=0.01
UNET D1D2 QTol=0.1
UNET D1D2 MinQTol=1
Write IC File= 0
Write IC File at Fixed DateTime=0
Write IC File at Sim End=0
Echo Input=False
Echo Parameters=False
Echo Output=False
Write Detailed= 0
HDF Write Warmup=0
HDF Write Time Slices=0
HDF Flush=0
HDF Compression= 1
HDF Chunk Size= 1
HDF Spatial Parts= 1
HDF Use Max Rows=0
HDF Fixed Rows= 1
Calibration Method= 0
Calibration Iterations= 20
Calibration Max Change=0.05
Calibration Tolerance=0.2
Calibration Maximum=1.5
Calibration Minimum=0.5
Calibration Optimization Method= 1
WQ AD Non Conservative
WQ ULTIMATE=-1
WQ Max Comp Step=1HOUR
WQ Output Interval=15MIN
WQ Output Selected Increments= 0
WQ Output face flow=0
WQ Output face velocity=0
WQ Output face area=0
WQ Output face dispersion=0
WQ Output cell volume=0
WQ Output cell surface area=0
WQ Output cell continuity=0
WQ Output cumulative cell continuity=0
WQ Output face conc=0
WQ Output face dconc_dx=0
WQ Output face courant=0
WQ Output face peclet=0
WQ Output face adv mass=0
WQ Output face disp mass=0
WQ Output cell mass=0
WQ Output cell source sink temp=0
WQ Output nsm pathways=0
WQ Output nsm derived pathways=0
WQ Create Restart=0
WQ Fixed Restart=0
WQ System Summary=0
WQ Write To DSS=0
Sorting and Armoring Iterations= 10
XS Update Threshold= 0.02
Bed Roughness Predictor= 0
Hydraulics Update Threshold= 0.02
Energy Slope Method= 1
Volume Change Method= 1
Sediment Retention Method= 0
Sediment TS Multiplier= 1
Warm Up Method= 0
XS Weighting Method= 0
Number of US Weighted Cross Sections= 1
Number of DS Weighted Cross Sections= 1
Upstream XS Weight=0
Main XS Weight=1
Downstream XS Weight=0
Number of DS XS's Weighted with US Boundary= 1
Upstream Boundary Weight= 1
Weight of XSs Associated with US Boundary= 0
Number of US XS's Weighted with DS Boundary= 1
Downstream Boundary Weight= 0.5
Weight of XSs Associated with DS Boundary= 0.5
Percentile Method= 0
Sediment Output Level= 3
Mass or Volume Output= 0
Output Increment Type= 1
Profile and TS Output Increment= 1
Transport Output Increment 1
XS Output Flag= 0
XS Output Increment= 10
Read HDF5 Sediment Hotstart= 0
Sediment Hotstart Type= 0
Write Gradation File= 0
Read Gradation Hotstart= 0
Write HDF5 File= 1
Write Binary Output= 1
Write DSS Sediment File= 0
DSS Sediment Output Type= 1
SV Curve= 0
Specific Gage Flag= 0
Subcell Erosion Methods= 0
Subcell Deposition Methods= 0
Advection Scheme= 1
Matrix Solver= 0
Implicit Weighting Factor= 1
Maximum Outer Loop Convergence Iterations= 5
Convergence Maximum Absolute= 0.001
Convergence RMSE= 0.0001
Grain Fractions Max Abs Error= 0.001
Max Subgrid Regions= 1
Max Subgrid Length Scale= 3.402823E+38
Initial Layer Thickness= 3.402823E+38
Min Layer Thickness= 3.402823E+38
Max Layer Thickness= 3.402823E+38
Number of Layers= 5

--- CUPRN.f01 (steady flow) ---

Flow Title=Flow
Program Version=6.00
Number of Profiles= 6
Profile Names=01pct,10pct,04pct,02pct,0_2pct,01plus
River Rch & RM=CUPRN,Main,4186
     767     410     542     651    1060    1130
Boundary for River Rch & Prof#=CUPRN,Main            , 1
Up Type= 0
Dn Type= 3
Dn Slope=0.02774
Boundary for River Rch & Prof#=CUPRN,Main            , 2
Up Type= 0
Dn Type= 3
Dn Slope=0.02774
Boundary for River Rch & Prof#=CUPRN,Main            , 3
Up Type= 0
Dn Type= 3
Dn Slope=0.02774
Boundary for River Rch & Prof#=CUPRN,Main            , 4
Up Type= 0
Dn Type= 3
Dn Slope=0.02774
Boundary for River Rch & Prof#=CUPRN,Main            , 5
Up Type= 0
Dn Type= 3
Dn Slope=0.02774
Boundary for River Rch & Prof#=CUPRN,Main            , 6
Up Type= 0
Dn Type= 3
Dn Slope=0.02774
DSS Import GetInterval= 0
DSS Import GetPeak= 0
DSS Import FillOption= 0

--- CUPRN.g01 (geometry) ---

Geom Title=Geometry
Program Version=6.10

River Reach=CUPRN           ,Main
Reach XY= 30
     2248396.615      518393.8572248344.20916301518309.232423214
     2248350.212      518061.1692248296.91804814517964.299618955
2248221.80957823517882.651854404 2248150.8115221517761.207811023
2248074.20835628517698.8042564242248020.39930321517672.647077849
     2247800.596      517664.613     2247713.083      517613.228
     2247581.139       517497.76     2247555.013      517453.376
     2247538.891       517332.82     2247517.185      517275.626
      2247314.07      517028.704     2247280.486      516898.432
     2247229.864      516812.1822247156.46506229516774.895341774
      2246808.56      516707.075     2246665.451      516605.917
     2246461.083      516590.7972246360.18360136516525.711619631
 2246152.1215171516451.0490220992245972.88399577516364.906504086
2245816.06815321516372.465418532      2245745.87       516354.24
  2245673.163299516320.1566007442245560.65103764516216.614565235
      2245451.08      516141.261     2245398.534      516123.772

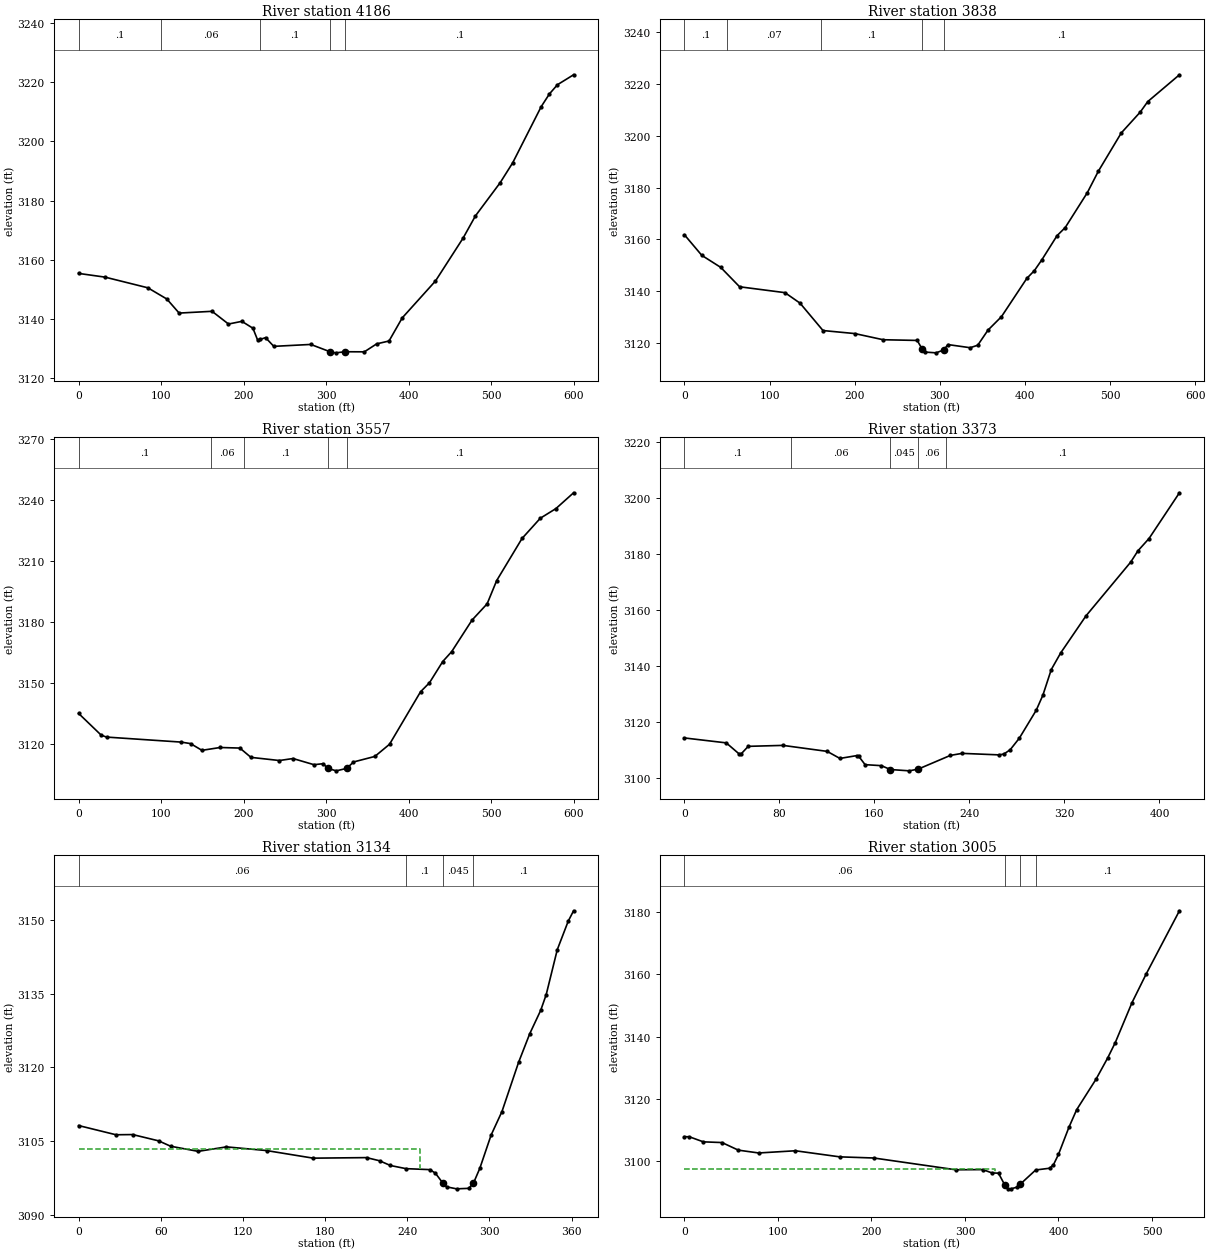
Type RM Length L Ch R = 1 ,4186    ,347.9,347.9,347.9
XS GIS Cut Line= 2
2248645.91735145518203.1274648292248164.71473048518561.078379462
#Sta/Elev= 30
       0 3155.42    32.1 3154.16    83.9 3150.56   106.9 3146.77   121.8 3142.02
   161.7 3142.62   181.6 3138.32   197.8 3139.23   211.2  3136.9   217.1 3132.77
     220 3133.12   226.5 3133.73   236.5 3130.78   281.3 3131.43     305 3128.92
   311.5 3128.59   322.9 3128.96   346.2 3128.93   361.1 3131.62   376.1 3132.59
   392.1  3140.4   432.4 3152.87   465.9 3167.38   480.8 3174.86   510.7 3186.04
   525.9 3192.77   560.5 3211.77   570.5 3216.08   580.2 3219.17   599.7 3222.52
#Mann= 5 ,-1,0
       0      .1       0     100     .06       0     220      .1       0
     305    .045       0   322.9      .1       0
Bank Sta=305,322.9
XS Rating Curve= 0 ,0
Exp/Cntr(USF)=0,0
Exp/Cntr=0.3,0.1

Type RM Length L Ch R = 1 ,3838    ,282.5,280.8,271.7
XS GIS Cut Line= 2
2248610.51457061517934.1777474442248086.67589201 518186.89014581
#Sta/Elev= 30
       0 3161.78    20.4 3153.84    42.6 3149.21    64.8 3141.71   118.1 3139.44
   135.8 3135.39   162.8 3124.81   200.2 3123.64   233.5 3121.26   273.5 3120.99
   279.6 3117.49   282.4  3116.5   295.7  3116.2   304.6 3117.31   309.6 3119.39
   335.7 3118.18   344.6 3119.14   356.7 3124.99   372.5 3130.17   402.3 3144.96
   411.2 3147.96   420.1  3152.2   437.8 3161.45   447.4 3164.57   473.4 3178.06
   486.3 3186.32   513.3 3201.13   535.5 3209.15   544.4 3213.23   581.6 3223.58
#Mann= 5 ,-1,0
       0      .1       0      50     .07       0     160      .1       0
   279.6    .045       0   304.6      .1       0
Bank Sta=279.6,304.6
XS Rating Curve= 0 ,0
Exp/Cntr(USF)=0,0
Exp/Cntr=0.3,0.1

Type RM Length L Ch R = 1 ,3557    ,184.5,183.7,180.8
XS GIS Cut Line= 2
2248424.57201693517626.5138907192247978.20706829518027.460685979
#Sta/Elev= 30
       0 3135.27    27.4 3124.58    33.9 3123.64   124.2 3121.18   135.7 3120.44
   149.5 3117.13   171.6 3118.52   195.5 3118.24   208.9 3113.67   243.4 3112.12
   259.9  3113.1   285.3 3110.07   296.3 3110.56   302.4 3108.21   312.4 3107.05
   325.1 3108.27   333.2  3111.4   359.1 3114.13   376.9 3120.11   414.5 3145.91
   425.3 3150.32   441.4 3160.77   452.2 3165.61   476.9 3181.13   495.2 3189.12
   506.8 3200.57   537.5 3221.24   559.7  3231.2   578.6 3235.93     600  3243.7
#Mann= 5 ,-1,0
       0      .1       0     160     .06       0     200      .1       0
   302.4    .045       0   325.1      .1       0
Bank Sta=302.4,325.1
XS Rating Curve= 0 ,0
Exp/Cntr(USF)=0,0
Exp/Cntr=0.3,0.1

Type RM Length L Ch R = 1 ,3373    ,247.4,239.7,229.3
XS GIS Cut Line= 2
2248191.54805465517566.6671109192247917.18345129517880.408115685
#Sta/Elev= 30
       0 3114.24    35.2 3112.48    45.8 3108.62    47.7 3108.53    53.7 3111.24
      83 3111.58   120.2 3109.44   130.9 3106.92   144.9 3107.92   146.8 3107.66
   152.1  3104.7   165.8 3104.34   173.4 3102.96   189.3 3102.49   196.9 3103.12
   223.9    3108   233.8 3108.73     265 3108.19     269  3108.5   274.3 3110.03
     282 3114.16   296.2 3124.12   301.8 3129.49   308.9 3138.68   316.8  3144.6
   338.1 3157.84   375.8 3177.07   381.9 3181.11   391.2 3185.48   416.8 3201.82
#Mann= 5 ,-1,0
       0      .1       0      90     .06       0   173.4    .045       0
   196.9     .06       0     220      .1       0
Bank Sta=173.4,196.9
XS Rating Curve= 0 ,0
Exp/Cntr(USF)=0,0
Exp/Cntr=0.3,0.1

Type RM Length L Ch R = 1 ,3134    ,119.6,128.9,134.6
BEGIN DESCRIPTION:
structure xs 4
END DESCRIPTION:
XS GIS Cut Line= 3
2248070.12227045517539.4212441192247849.62095347517631.883224567
2247831.55485109517752.969462887
#Sta/Elev= 30
       0 3108.19    27.3 3106.32    39.5 3106.36    58.5 3105.08    67.2 3103.99
    87.3 3102.95     108 3103.86   137.3 3103.11   171.3 3101.57   210.3 3101.68
   219.8 3101.04   227.7 3100.08   239.1 3099.44   256.6 3099.24   260.6 3098.51
   266.1 3096.48   268.7 3095.75     276 3095.34   284.9 3095.44288.34593096.477
     293 3099.49   301.3 3106.28   309.2 3111.04   321.3    3121   329.5 3126.85
   337.5 3131.59   341.5 3134.77   349.6 3143.91   357.6  3149.7   361.5  3151.8
#Mann= 4 ,-1,0
       0     .06       0   239.1      .1       0   266.1    .045       0
288.3459      .1       0
#XS Ineff= 2 , 0
          249.69 3103.37
Permanent Ineff=
       F       F
Bank Sta=266.1,288.3459
XS Rating Curve= 0 ,0
Exp/Cntr(USF)=0,0
Exp/Cntr=0.5,0.3

Type RM Length L Ch R = 1 ,3005    ,124,131.3,140.6
BEGIN DESCRIPTION:
structure xs 3; 10.2 ft between structure and xs
END DESCRIPTION:
XS GIS Cut Line= 6
2248057.01902364517535.4554896722247863.82963499517619.314062308
 2247783.1547297517615.7392243332247740.23553184517604.905252058
2247707.73361502517649.074523641 2247672.6888171517783.510508159
#Sta/Elev= 30
       0 3107.83     5.3 3107.78    20.2 3106.16    40.2 3105.93    57.6 3103.49
    79.4 3102.58   118.7 3103.29   166.1 3101.33   202.6 3100.96   290.3 3097.17
   319.2 3097.23   328.9 3096.16   335.9 3096.08   342.5 3092.32   345.9 3091.05
   349.2 3091.04   355.8 3091.59   358.8 3092.44   375.7 3097.11   390.6 3097.67
   394.7 3098.81     400 3102.09   411.2 3110.83   419.5 3116.51   440.2 3126.31
   452.6 3133.11   460.8  3138.1   478.7 3150.96   493.9  3160.2   529.4  3180.5
#Mann= 4 ,-1,0
       0     .06       0   342.5    .045       0   358.8     .06       0
  375.62      .1       0
#XS Ineff= 2 , 0
           332.3  3097.3     370          3094.7
Permanent Ineff=
       F       F
Bank Sta=342.5,358.8
XS Rating Curve= 0 ,0
Exp/Cntr(USF)=0,0
Exp/Cntr=0.5,0.3

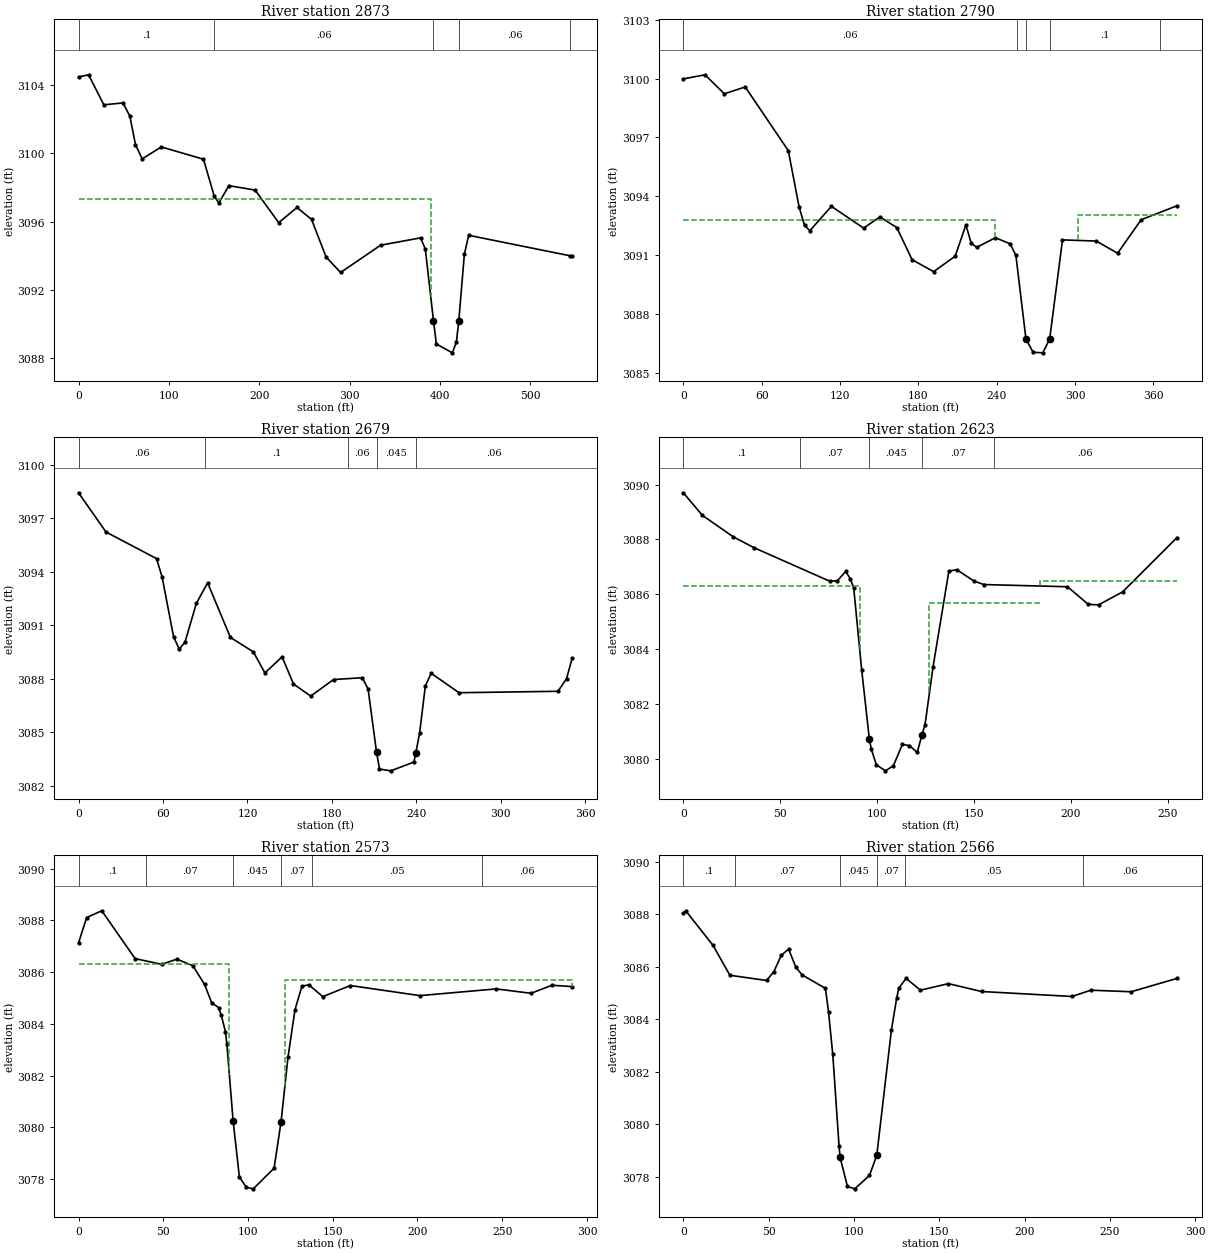
Type RM Length L Ch R = 1 ,2873    ,81.8,83,80.6
BEGIN DESCRIPTION:
structure xs 2; 8.3 ft between structure and xs
END DESCRIPTION:
XS GIS Cut Line= 5
2248018.62393441517483.2254386382247834.26010037517548.172108534
2247648.56345875517527.4006811672247603.56080468517549.068625717
2247490.61028815517531.941246881
#Sta/Elev= 30
       0 3104.48    11.1 3104.61      28 3102.85    49.2 3102.96    56.8 3102.19
      63 3100.52    70.5 3099.68    91.7 3100.38   138.3 3099.66   150.3 3097.48
   155.3  3097.1   166.5 3098.11   195.5 3097.85   221.6 3095.94   241.8 3096.83
     258 3096.13     274 3093.93   290.1 3093.02   334.4 3094.62   378.7 3095.05
   383.9 3094.39392.94993090.187   396.1 3088.83   413.8 3088.31   418.3 3088.94
  420.99  3090.2   427.1 3094.08   431.9  3095.2   544.1    3094   546.5 3093.96
#Mann= 5 ,-1,0
       0      .1       0   150.3     .06       0392.9499    .045       0
  420.99     .06       0   544.1      .1       0
#XS Ineff= 2 ,-1
       0     390  3097.3     426   538.6  3091.2
Permanent Ineff=
       F       F
Bank Sta=392.9499,420.99
XS Rating Curve= 0 ,0
Exp/Cntr(USF)=0,0
Exp/Cntr=0.5,0.3

Type RM Length L Ch R = 1 ,2790    ,108,111.5,114.7
BEGIN DESCRIPTION:
structure xs 1
END DESCRIPTION:
XS GIS Cut Line= 3
2247830.20961953517409.1819306462247601.89712238517465.875495352
2247471.94056731517525.252197236
#Sta/Elev= 30
       0 3099.98    16.6 3100.19    31.4 3099.22    47.4 3099.57    80.4 3096.32
    88.6 3093.47    92.8 3092.51    96.9 3092.24   113.4 3093.48   138.1 3092.37
   150.5 3092.94   163.5  3092.4   175.2 3090.76   191.7 3090.15   208.2 3090.94
   216.4 3092.53   220.5  3091.6   224.7 3091.39     239 3091.88   250.3 3091.57
   254.7 3090.98   262.4 3086.72   267.9 3086.04   275.3 3086.01   280.6 3086.72
   290.4 3091.77   316.3 3091.71   332.6 3091.09   350.7  3092.8   378.1 3093.51
#Mann= 5 ,-1,0
       0     .06       0  255.25      .1       0   262.4    .045       0
   280.6      .1       0  365.25     .06       0
#XS Ineff= 2 , 0
          238.65 3092.76   302.2         3093.06
Permanent Ineff=
       F       F
Bank Sta=262.4,280.6
XS Rating Curve= 0 ,0
Exp/Cntr(USF)=0,0
Exp/Cntr=0.3,0.1

Type RM Length L Ch R = 1 ,2679    ,56.2,55.7,55.1
BEGIN DESCRIPTION:
structure xs 4
END DESCRIPTION:
XS GIS Cut Line= 4
 2247767.0505371517364.2604547022247666.87539991517350.483036975
 2247515.0452714517379.389610237 2247449.1897474517447.833292295
#Sta/Elev= 30
       0 3098.43    19.5 3096.23    55.4 3094.74    59.4  3093.7    67.5 3090.36
    71.5 3089.67    75.6 3090.05    83.7 3092.23    91.7 3093.38   107.9 3090.32
   124.2 3089.51   132.4 3088.33   144.6 3089.23   152.7 3087.71   164.9 3087.03
   181.2 3087.96   201.6 3088.06   205.7 3087.43   211.73083.885   213.8 3082.94
   221.8 3082.84   238.2 3083.33  239.553083.817   242.3 3084.96   246.4 3087.61
   250.5 3088.31   270.3 3087.22   340.6  3087.3   346.7 3088.01   350.7 3089.16
#Mann= 5 ,-1,0
       0     .06       0      90      .1       0  191.12     .06       0
   211.7    .045       0  239.55     .06       0
Bank Sta=211.7,239.55
XS Rating Curve= 0 ,0
Exp/Cntr(USF)=0,0
Exp/Cntr=0.5,0.3

Type RM Length L Ch R = 1 ,2623    ,49.5,50.2,49.4
BEGIN DESCRIPTION:
structure xs 3; 4.8 ft between structure and xs
END DESCRIPTION:
XS GIS Cut Line= 4
2247632.92495426517281.8382350312247575.66830456517310.054224883
2247491.40567206517328.5896201742247423.25181977517407.969426796
#Sta/Elev= 30
       0  3089.7     9.8 3088.88    25.7  3088.1    36.5  3087.7    75.6 3086.48
    79.5  3086.5    83.8 3086.84    86.2 3086.56    87.9 3086.24      92 3083.26
95.961673080.738      97 3080.36    99.6  3079.8   104.3 3079.58   108.4 3079.77
     113 3080.54   116.6  3080.5   120.7 3080.25   123.1 3080.89   124.7 3081.26
   128.8 3083.35     137 3086.85   141.1  3086.9   150.1 3086.48   155.1 3086.36
   198.2 3086.28   208.9 3085.64   214.2 3085.62   226.6 3086.09   254.7 3088.07
#Mann= 5 ,-1,0
       0      .1       0      60     .07       095.96167    .045       0
   123.1     .07       0  160.11     .06       0
#XS Ineff= 3 ,-1
       0    91.1  3086.3     127  184.23  3085.7  184.23   254.7 3086.49
Permanent Ineff=
       F       F       F
Bank Sta=95.96167,123.1
XS Rating Curve= 0 ,0
Exp/Cntr(USF)=0,0
Exp/Cntr=0.5,0.3

Type RM Length L Ch R = 1 ,2573    ,11.1,6.9,4.7
BEGIN DESCRIPTION:
structure xs 2; 6.7 ft between structure and xs
END DESCRIPTION:
XS GIS Cut Line= 3
2247616.53701765517237.0214791282247564.25054002517261.956490477
2247336.38852544517312.592493717
#Sta/Elev= 30
       0 3087.13     4.8 3088.11    13.7 3088.37    33.4 3086.52    49.1  3086.3
      58  3086.5    67.4 3086.25    74.4 3085.52    78.5 3084.82    82.6 3084.63
    84.2 3084.34    86.7 3083.69    87.5 3083.23    91.2 3080.26    94.9 3078.08
      99 3077.68   103.1 3077.62   115.4 3078.42   119.5 3080.21   123.6 3082.71
   127.7 3084.54   131.8 3085.45   135.9 3085.51   144.1 3085.05   160.4 3085.48
   201.4 3085.09   246.5 3085.35     267 3085.18   279.3 3085.49   291.3 3085.44
#Mann= 6 ,-1,0
       0      .1       0      40     .07       0    91.2    .045       0
   119.5     .07       0  137.93     .05       0  237.93     .06       0
#XS Ineff= 2 , 0
              89  3086.3   121.7          3085.7
Permanent Ineff=
       F       F
Bank Sta=91.2,119.5
XS Rating Curve= 0 ,0
Exp/Cntr(USF)=0,0
Exp/Cntr=0.5,0.3

Type RM Length L Ch R = 1 ,2566    ,9.6,6.5,4.9
BEGIN DESCRIPTION:
structure xs 4/1
END DESCRIPTION:
XS GIS Cut Line= 3
2247609.51595793517227.9575612792247484.66060188517277.755362248
2247333.10207719 517309.99161988
#Sta/Elev= 30
       0 3088.04     1.4 3088.14    17.4 3086.82    27.3 3085.68    48.8 3085.48
    53.1 3085.82    57.4 3086.44    61.7 3086.68      66 3085.98    69.7 3085.69
    83.3 3085.18    85.1 3084.29    87.6 3082.66    91.3 3079.15    91.9 3078.73
    96.2 3077.62   100.5 3077.53   109.1 3078.04   113.4 3078.81     122  3083.6
   125.1 3084.82   126.3 3085.19   130.6 3085.56     139 3085.11   155.4 3085.36
   174.8 3085.06   227.8 3084.87   238.9 3085.11   262.5 3085.05   289.4 3085.56
#Mann= 6 ,-1,0
       0      .1       0      30     .07       0    91.9    .045       0
   113.4     .07       0     130     .05       0  234.42     .06       0
Bank Sta=91.9,113.4
XS Rating Curve= 0 ,0
Exp/Cntr(USF)=0,0
Exp/Cntr=0.5,0.3

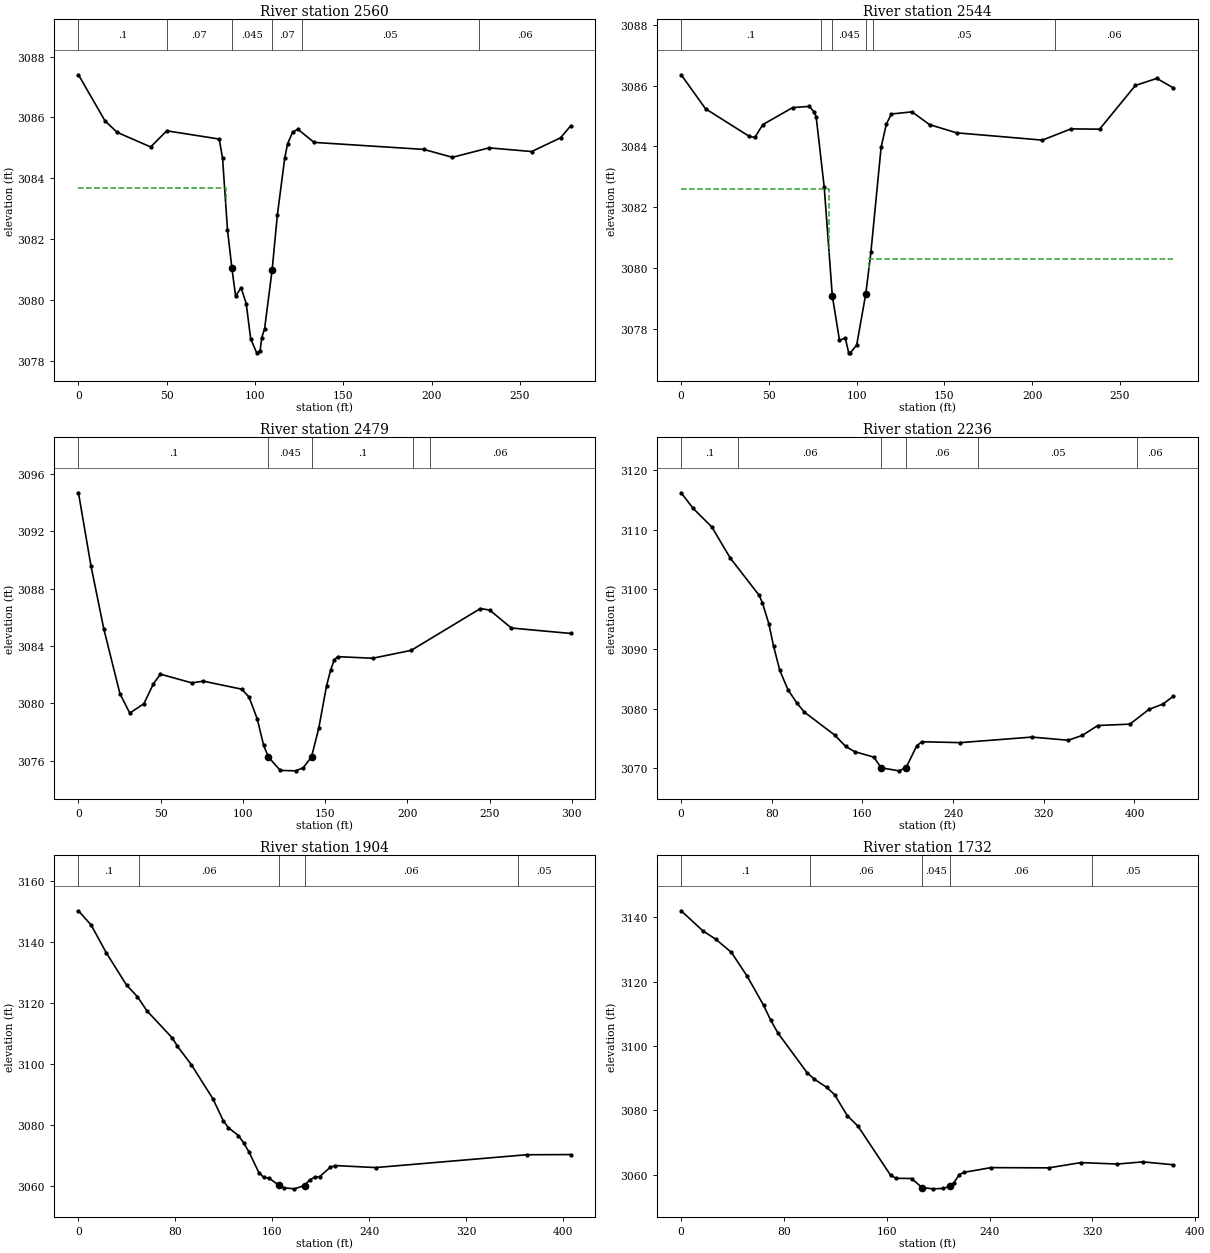
Type RM Length L Ch R = 1 ,2560    ,16.1,15.9,16
BEGIN DESCRIPTION:
structure xs 3; 3.5 ft between structure and xs
END DESCRIPTION:
XS GIS Cut Line= 4
2247598.28695011517223.3162092382247534.27253932517246.379746963
2247483.69832553517275.830809553  2247334.567661517306.074139938
#Sta/Elev= 30
       0  3087.4      15 3085.89    21.9 3085.51    40.9 3085.03      50 3085.56
    79.7 3085.29    81.6 3084.66    84.4 3082.3186.900373081.045      89 3080.13
    92.1 3080.41      95 3079.89    97.5 3078.74   100.9 3078.27   102.9 3078.34
   103.8 3078.77   105.4 3079.06   109.7    3081   112.6 3082.78   116.8 3084.66
   118.4 3085.13   121.4 3085.53   124.3 3085.61   133.4 3085.18   195.5 3084.95
   211.8 3084.69   232.5    3085   256.7 3084.88     273 3085.33   278.7 3085.72
#Mann= 6 ,-1,0
       0      .1       0      50     .07       086.90037    .045       0
   109.7     .07       0  126.57     .05       0  226.57     .06       0
#XS Ineff= 2 , 0
            83.4 3083.67   113.1         3081.47
Permanent Ineff=
       F       F
Bank Sta=86.90037,109.7
XS Rating Curve= 0 ,0
Exp/Cntr(USF)=0,0
Exp/Cntr=0.5,0.3

Type RM Length L Ch R = 1 ,2544    ,63.8,64.9,65.1
BEGIN DESCRIPTION:
structure xs 2; 5.4 ft between structure and xs
END DESCRIPTION:
XS GIS Cut Line= 4
2247587.86131138517211.0277179312247522.60499887517234.712206518
 2247467.7946926517266.7301082052247322.90012056517294.406599493
#Sta/Elev= 30
       0 3086.36    13.9 3085.24    38.9 3084.33      42  3084.3    46.5 3084.72
    63.5 3085.28      73 3085.32    75.9 3085.12    76.9 3084.98    81.5 3082.66
    86.1 3079.09    90.2 3077.62    93.5  3077.7    95.4 3077.22    96.4 3077.21
     100 3077.47   105.2 3079.16   108.1 3080.52   113.9 3083.97   116.9 3084.74
   119.8 3085.07   131.5 3085.14   141.5 3084.72   156.9 3084.45   205.8 3084.21
   222.1 3084.58   238.4 3084.57   258.8 3086.01     271 3086.24   280.4 3085.93
#Mann= 6 ,-1,0
       0      .1       0   79.42     .07       0    86.1    .045       0
   105.2     .07       0  109.42     .05       0   212.9     .06       0
#XS Ineff= 2 , 0
            84.3  3082.6     107          3080.3
Permanent Ineff=
       F       F
Bank Sta=86.1,105.2
XS Rating Curve= 0 ,0
Exp/Cntr(USF)=0,0
Exp/Cntr=0.5,0.3

Type RM Length L Ch R = 1 ,2479    ,241.9,242.6,247.6
BEGIN DESCRIPTION:
structure xs 1
END DESCRIPTION:
XS GIS Cut Line= 3
2247540.11484443517110.4857735612247502.18907582517173.473246455
2247309.33678502517290.773433974
#Sta/Elev= 30
       0 3094.69     7.6 3089.59    15.4 3085.19    25.2 3080.67    31.2 3079.31
    39.8 3079.97    45.6 3081.36    49.8 3082.03    68.9 3081.42    75.9 3081.54
    99.3 3080.98   103.7 3080.43   108.7  3078.9   112.6 3077.05   115.5 3076.24
   122.7 3075.31   132.1 3075.28   136.7  3075.5   141.7 3076.26   146.1 3078.26
   150.8  3081.2   153.4 3082.35   155.5 3083.02   157.6 3083.25   178.9 3083.14
   202.3 3083.69   244.4 3086.61     250  3086.5   263.2 3085.25   299.2 3084.87
#Mann= 5 ,-1,0
       0      .1       0   115.5    .045       0   141.7      .1       0
  203.52     .05       0  213.52     .06       0
Bank Sta=115.5,141.7
XS Rating Curve= 0 ,0
Exp/Cntr(USF)=0,0
Exp/Cntr=0.3,0.1

Type RM Length L Ch R = 1 ,2236    ,346.1,332.2,317
XS GIS Cut Line= 4
2247451.95232231516911.770845017 2247365.7303738516991.774800411
2247238.48470472517036.0341635662247184.31319649517209.753652598
#Sta/Elev= 30
       0 3116.17    10.6 3113.54      27 3110.45    43.3 3105.23    68.8 3098.98
    71.6 3097.77    77.3 3094.24    81.5 3090.48      87  3086.4    94.2 3083.17
     102 3080.94   108.8 3079.38   135.7 3075.52   145.1 3073.64   153.1 3072.77
   170.1 3071.84176.46823070.058   192.2 3069.55198.46823070.085   207.9 3073.75
   212.4 3074.43   246.3 3074.28   309.4 3075.21   341.5 3074.68   354.1  3075.5
   367.6 3077.15     396 3077.38   412.8 3079.85   425.3 3080.76   434.3 3082.06
#Mann= 6 ,-1,0
       0      .1       0      50     .06       0176.4682    .045       0
198.4682     .06       0  262.34     .05       0  402.34     .06       0
Bank Sta=176.4682,198.4682
XS Rating Curve= 0 ,0
Exp/Cntr(USF)=0,0
Exp/Cntr=0.3,0.1

Type RM Length L Ch R = 1 ,1904    ,173.8,172.5,171.6
XS GIS Cut Line= 3
2247179.46707984516599.3345315582247099.58601064516849.854046071
2247095.27209177516993.237992611
#Sta/Elev= 30
       0 3150.38    10.5 3145.68    22.9 3136.63    39.7 3125.96    48.7 3122.16
    56.5 3117.53    77.5 3108.58    81.7 3105.89    93.2 3099.82   111.1 3088.56
   119.5 3081.47   123.7 3079.16   132.1 3076.51   136.3 3074.19     141 3071.01
   148.9 3064.38   153.1 3062.77   157.3 3062.55   165.7 3060.15   169.9 3059.35
   178.3 3059.02   186.7 3060.11   190.9 3061.96   195.1 3062.82   199.3 3063.06
   207.8 3066.05   211.9 3066.67   245.4 3066.01   370.1 3070.22   406.4 3070.28
#Mann= 5 ,-1,0
       0      .1       0      50     .06       0   165.7    .045       0
   186.7     .06       0  362.95     .05       0
Bank Sta=165.7,186.7
XS Rating Curve= 0 ,0
Exp/Cntr(USF)=0,0
Exp/Cntr=0.3,0.1

Type RM Length L Ch R = 1 ,1732    ,132,132.6,133.3
XS GIS Cut Line= 3
2247069.50582843516572.3461039492246966.25274734516693.883584824
2246913.55065386  516911.1452763
#Sta/Elev= 30
       0 3142.03    16.8 3135.82    27.1 3133.13    39.1 3129.09    51.5 3121.61
    64.1 3112.67    69.6  3108.1    75.3 3104.03      98 3091.72   103.7 3089.68
   113.3 3087.16   119.4 3084.88   129.2  3078.4   137.6 3075.11   162.9 3059.89
     167 3058.91   179.3 3058.84   187.4 3056.04   195.8 3055.63     204 3055.75
   209.23056.435   212.3 3057.57   216.4 3060.07   220.2 3060.76   241.1 3062.22
   286.1 3062.15     311 3063.78   339.5 3063.34   359.4 3064.01     383 3063.11
#Mann= 5 ,-1,0
       0      .1       0     100     .06       0   187.4    .045       0
   209.2     .06       0  319.48     .05       0
Bank Sta=187.4,209.2
XS Rating Curve= 0 ,0
Exp/Cntr(USF)=0,0
Exp/Cntr=0.3,0.1

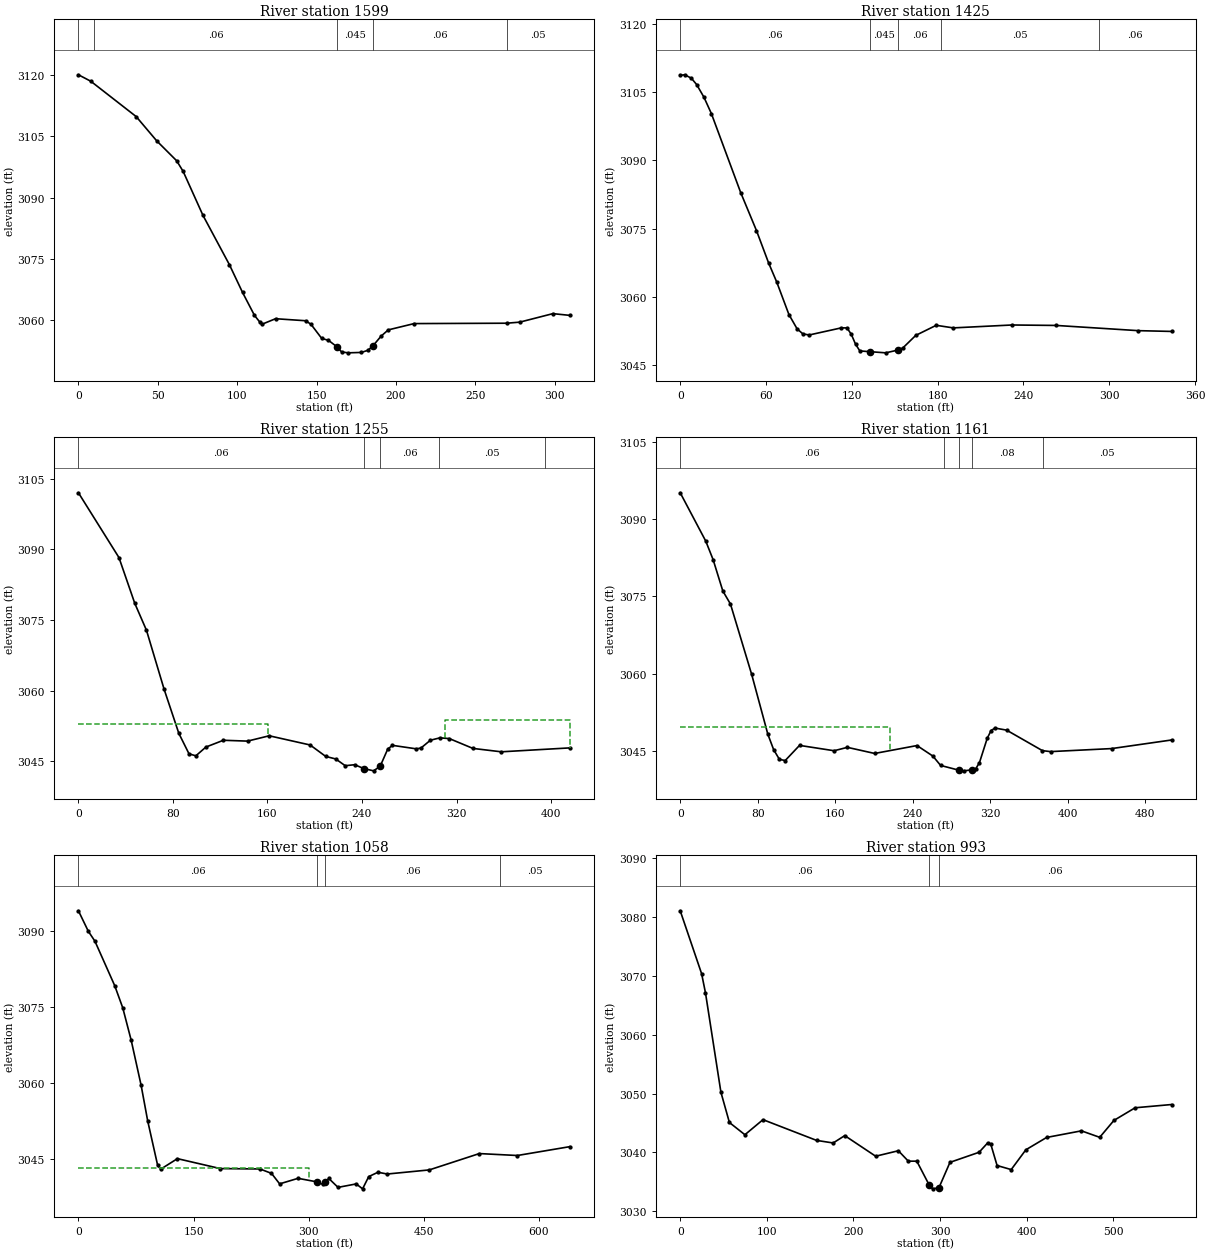
Type RM Length L Ch R = 1 ,1599    ,171,174,176.8
XS GIS Cut Line= 2
2246873.49306941516545.6297125672246789.42714674516843.479958513
#Sta/Elev= 30
       0    3120     7.8 3118.42    36.4 3109.78    49.3 3103.86    61.9 3098.98
      66 3096.37    78.5 3085.61    95.1  3073.6   103.4  3066.8   110.9  3061.2
   114.2 3059.59   115.9 3059.07   124.2 3060.38   143.3 3059.88   146.6 3058.97
   153.3 3055.55   157.5 3055.11 162.9813053.473   165.8 3052.26   169.9 3052.04
   178.3 3052.14   182.4 3052.67185.48043053.723   190.7 3056.13   195.2 3057.65
   211.5 3059.19   269.7 3059.28     278 3059.54   298.9 3061.62   309.5  3061.2
#Mann= 5 ,-1,0
       0      .1       0      10     .06       0 162.981    .045       0
185.4804     .06       0     270     .05       0
Bank Sta=162.981,185.4804
XS Rating Curve= 0 ,0
Exp/Cntr(USF)=0,0
Exp/Cntr=0.3,0.1

Type RM Length L Ch R = 1 ,1425    ,175.6,170.3,164.5
XS GIS Cut Line= 3
2246766.19990271516500.2840577662246701.66672702516579.874974445
2246599.48919885516798.212218849
#Sta/Elev= 30
       0 3108.77     3.2 3108.89     7.8 3108.13    11.5 3106.73    16.6 3103.94
    21.8 3100.33    42.3 3082.91    53.3 3074.56    61.8 3067.41    67.5 3063.19
      76 3056.04    81.7 3052.89    85.8 3051.76    90.2 3051.53   112.7  3053.1
   116.6 3053.08   119.6 3051.69   122.6 3049.49   125.6 3048.01   132.5 3047.85
   143.7 3047.59   152.6 3048.23   155.7 3048.68   164.7 3051.44     179 3053.66
   190.9 3053.09     232 3053.73   262.9 3053.63   320.3 3052.48   343.5 3052.31
#Mann= 5 ,-1,0
       0     .06       0   132.5    .045       0   152.6     .06       0
  182.47     .05       0  292.47     .06       0
Bank Sta=132.5,152.6
XS Rating Curve= 0 ,0
Exp/Cntr(USF)=0,0
Exp/Cntr=0.3,0.1

Type RM Length L Ch R = 1 ,1255    ,94.1,94,93.8
XS GIS Cut Line= 3
2246640.36021012  516390.57765912246519.89828217516556.212810027
2246510.21830582516767.021183934
#Sta/Elev= 30
       0 3102.02    34.3 3088.27    47.7 3078.55    57.6 3072.83    72.5 3060.33
      85 3050.94    93.6  3046.6    99.4 3046.18   107.9 3048.04   122.7 3049.48
   143.1  3049.3   161.5 3050.43   196.1 3048.48   209.3 3046.05   217.8 3045.51
   225.8 3044.08   233.8 3044.29   241.63043.471   249.8 3042.99   255.43043.967
   261.8 3047.62   265.8  3048.4     286 3047.66   289.9 3047.83   297.9 3049.49
   305.9 3049.99   313.9 3049.84   333.9 3047.75   357.9 3047.03   415.8 3047.86
#Mann= 5 ,-1,0
       0     .06       0   241.6    .045       0   255.4     .06       0
  304.81     .05       0  394.81     .06       0
#XS Ineff= 2 , 0
          160.56 3052.84  310.42         3053.68
Permanent Ineff=
       F       F
Bank Sta=241.6,255.4
XS Rating Curve= 0 ,0
Exp/Cntr(USF)=0,0
Exp/Cntr=0.3,0.1

Type RM Length L Ch R = 1 ,1161    ,102,102.9,103.5
XS GIS Cut Line= 4
2246605.94251642516385.1998944592246434.92960085516472.319681635
 2246425.2496245516634.7281737782246472.57395334516779.927819072
#Sta/Elev= 30
       0 3095.17    26.4 3085.76      34 3082.15      44 3076.07    51.9 3073.52
    73.8 3059.83    90.5 3048.19    96.5 3045.19   102.4 3043.32   108.4 3043.08
   123.2 3046.03   158.9 3044.99   172.6 3045.65   200.8 3044.46   244.5    3046
   260.9 3043.95   268.9 3042.13   287.9  3041.2     293 3041.08   300.9 3041.27
     305 3041.44     309 3042.68     317  3047.4     321 3048.92     325  3049.4
     337    3049     374 3045.01   382.4 3044.82   445.5 3045.41   507.3 3047.08
#Mann= 5 ,-1,0
       0     .06       0  271.93     .08       0   287.9    .045       0
   300.9     .08       0  374.62     .05       0
#XS Ineff= 2 , 0
          216.68 3049.63
Permanent Ineff=
       F       F
Bank Sta=287.9,300.9
XS Rating Curve= 0 ,0
Exp/Cntr(USF)=0,0
Exp/Cntr=0.3,0.1

Type RM Length L Ch R = 1 ,1058    ,61.3,64.3,67.5
XS GIS Cut Line= 4
2246580.20244437516362.2491078142246346.20249857516454.571610913
 2246338.0587312516611.7187707782246456.45202036516810.406561648
#Sta/Elev= 30
       0 3093.98    12.9 3089.94    21.5 3087.99    47.3 3079.22    57.8 3074.84
    68.8 3068.44    81.7 3059.59    90.3 3052.55   103.2 3043.84   107.1 3043.04
     129 3045.13   184.9 3043.17   236.5  3043.1   251.6 3042.23   262.2 3040.16
   286.2 3041.25   311.3 3040.54   318.3 3040.07  321.69 3040.54   326.3 3041.22
   338.3 3039.47     362 3040.15   370.3 3039.18   378.3 3041.59   390.3 3042.45
   402.4  3042.1   457.2 3042.91   522.4 3046.13     572 3045.75   640.2 3047.49
#Mann= 4 ,-1,0
       0     .06       0   311.3    .045       0  321.69     .06       0
  548.91     .05       0
#XS Ineff= 2 , 0
          299.91 3043.21
Permanent Ineff=
       F       F
Bank Sta=311.3,321.69
XS Rating Curve= 0 ,0
Exp/Cntr(USF)=0,0
Exp/Cntr=0.3,0.1

Type RM Length L Ch R = 1 ,993     ,62.8,63.1,63.4
XS GIS Cut Line= 4
2246518.28495278516351.1048666392246296.18327313516461.564152354
2246263.91668529516549.759492458 2246310.1654612516770.247842719
#Sta/Elev= 30
       0 3081.05    24.7 3070.37    29.2 3067.09      47 3050.23    56.8 3045.09
    74.7 3043.01    95.6 3045.57   157.4 3042.05   176.6 3041.61     190 3042.86
   225.7 3039.36   251.9 3040.29   263.4 3038.52   273.2 3038.52   287.63034.442
   291.4 3033.82   298.8 3034.02   311.5 3038.32   345.1 3040.03   355.2 3041.65
   358.6 3041.41   365.9 3037.78   382.2 3037.09   399.1 3040.45   423.1 3042.55
   463.3 3043.67   484.4 3042.57   500.8 3045.44   525.3 3047.59   567.3 3048.14
#Mann= 3 ,-1,0
       0     .06       0   287.6    .045       0   298.8     .06       0
Bank Sta=287.6,298.8
XS Rating Curve= 0 ,0
Exp/Cntr(USF)=0,0
Exp/Cntr=0.3,0.1