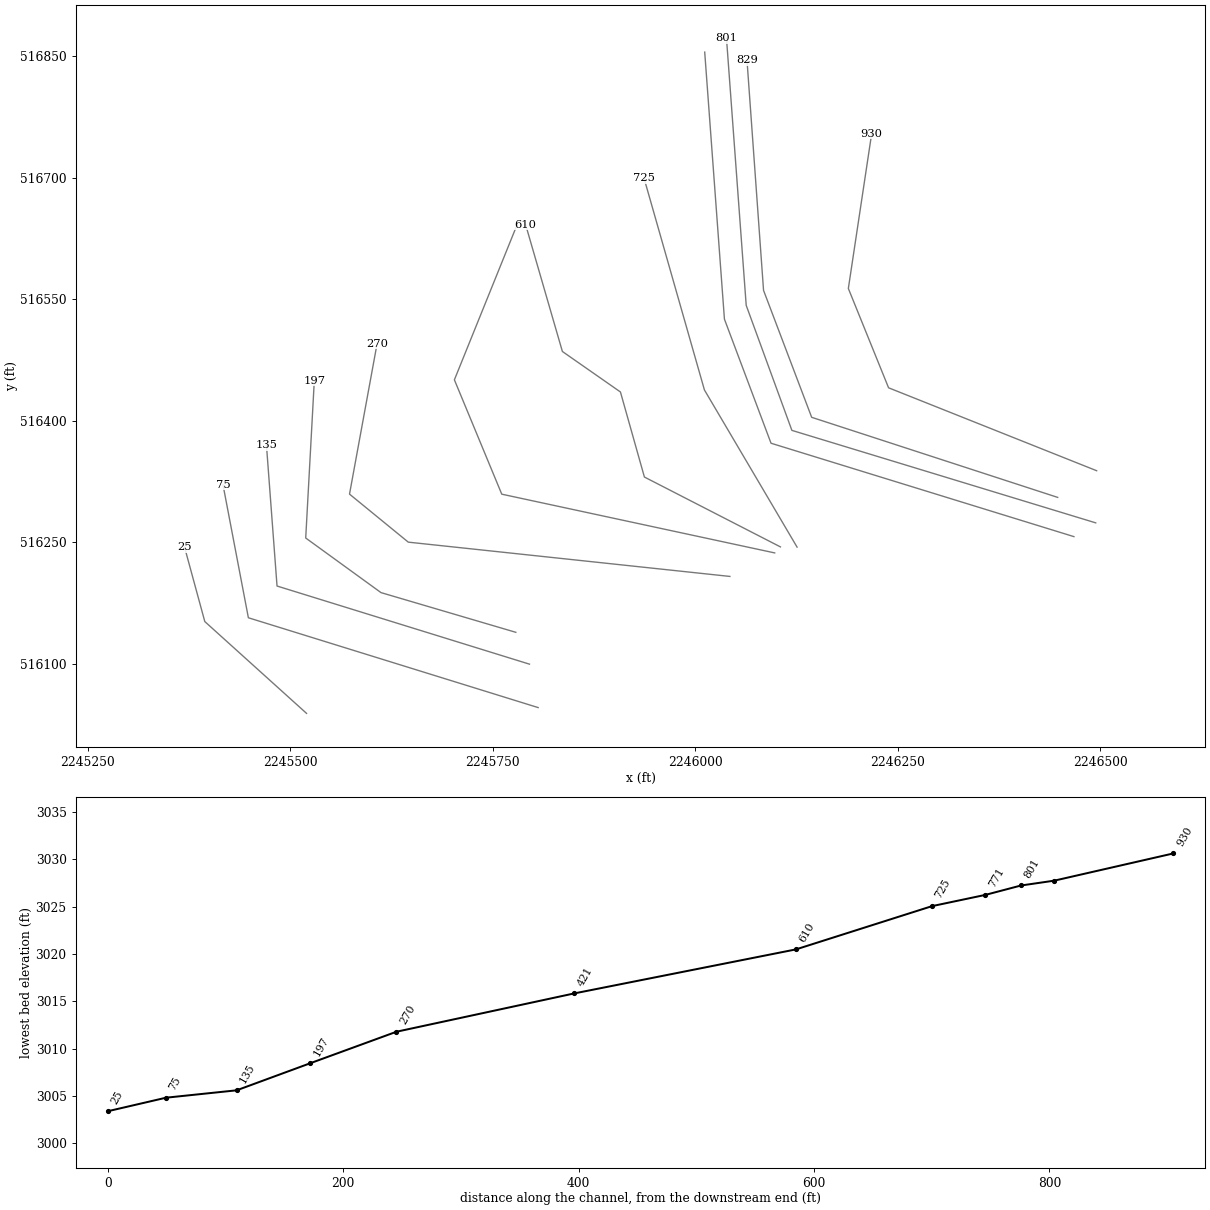
HEC-RAS study CUPRN.prj: CUPRN

--- CUPRN.g01 (geometry) --- (continued)

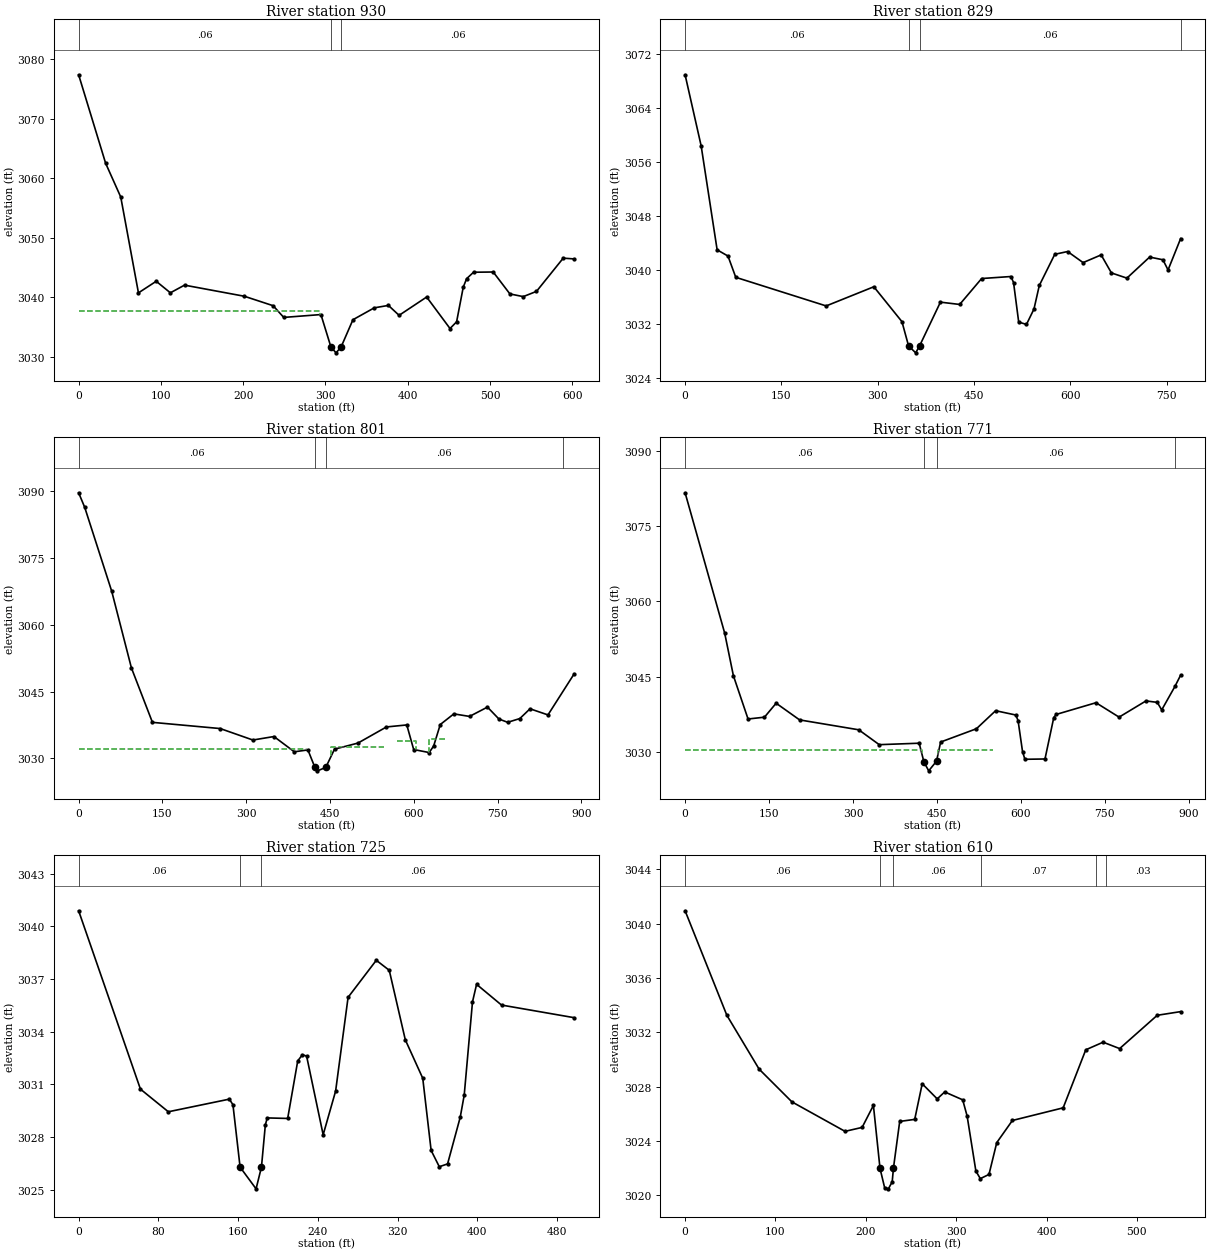
Type RM Length L Ch R = 1 ,930     ,101.4,101.3,101
XS GIS Cut Line= 4
 2246495.7390724516338.1150689342246238.86221311516440.497969891
2246189.20344079516563.1122225342246218.01779016516754.390456657
#Sta/Elev= 30
       0  3077.4    32.8 3062.52    51.2 3056.83    72.7 3040.71    94.3 3042.66
   111.5 3040.72   128.7 3042.01   201.4 3040.14   236.4 3038.55   249.3 3036.58
   294.5 3037.06  306.713031.576   312.9 3030.62     319  3031.6   333.4 3036.19
   359.3 3038.19   376.5  3038.6   389.5 3036.93     423 3040.01   451.4 3034.71
   459.4 3035.84   467.5 3041.68   471.6  3043.1     480 3044.18   503.9 3044.22
   524.2 3040.53   540.4 3040.08   556.5 3040.96     589 3046.55   602.3 3046.42
#Mann= 3 ,-1,0
       0     .06       0  306.71    .045       0     319     .06       0
#XS Ineff= 2 , 0
       0  293.13 3037.67               0
Permanent Ineff=
       F       F
Bank Sta=306.71,319
XS Rating Curve= 0 ,0
Exp/Cntr(USF)=0,0
Exp/Cntr=0.3,0.1

Type RM Length L Ch R = 1 ,829     ,28.6,28.2,28
BEGIN DESCRIPTION:
structure xs 4
END DESCRIPTION:
XS GIS Cut Line= 4
2246447.66124131516305.1788390232246143.92338167 516404.05181146
2246084.50967955516560.7634479822246064.08482459516844.668931931
#Sta/Elev= 30
       0 3068.94      25 3058.41    49.9    3043    66.8 3042.08    78.9 3038.93
   219.7 3034.69   293.9 3037.53   337.7 3032.36     348 3028.77   359.1 3027.74
  365.243028.784   397.6 3035.25   427.6 3034.91   461.8 3038.75   507.5 3039.05
   511.5 3038.15   519.5  3032.3   531.6 3031.95   543.3 3034.23   551.6 3037.72
   575.7 3042.34   595.7 3042.75   619.8 3041.11   647.9 3042.25   663.9 3039.58
     688 3038.81   723.4 3041.93   744.1 3041.53   752.1 3040.02   771.7 3044.67
#Mann= 4 ,-1,0
       0     .06       0     348    .045       0  365.24     .06       0
  771.66      .1       0
Bank Sta=348,365.24
XS Rating Curve= 0 ,0
Exp/Cntr(USF)=0,0
Exp/Cntr=0.5,0.3

Type RM Length L Ch R = 1 ,801     ,29.9,30.2,30.3
BEGIN DESCRIPTION:
structure xs 3; 13.4 ft between structure and xs
END DESCRIPTION:
XS GIS Cut Line= 4
2246494.57758076516273.7561322072246119.49037085 516387.92798477
2246063.09927258516542.2656433622246038.75406591516871.935308454
#Sta/Elev= 30
       0 3089.57    10.9  3086.3    59.2  3067.5    94.5  3050.3   132.1  3038.1
   253.4 3036.71   311.9 3034.14   349.6 3034.92   386.1  3031.5   410.4 3031.92
   422.73028.067   427.5 3027.23   442.4    3028     458 3032.09   499.9 3033.45
     551 3037.07   587.4 3037.52   599.7 3032.01   627.5 3031.33   635.5  3032.8
   647.3 3037.61   671.6    3040   699.7 3039.43   731.8 3041.52   752.3 3038.85
   767.9 3038.11   789.7 3038.95     808 3041.14   840.1 3039.77     887 3048.98
#Mann= 4 ,-1,0
       0     .06       0   422.7    .045       0   442.4     .06       0
   866.4      .1       0
#XS Ineff= 4 ,-1
   -1.42  407.873032.217  452.24  546.443032.597  570.17  604.46 3033.82
  627.41  656.48 3034.27
Permanent Ineff=
       F       F       F       F
Bank Sta=422.7,442.4
XS Rating Curve= 0 ,0
Exp/Cntr(USF)=0,0
Exp/Cntr=0.5,0.3

Type RM Length L Ch R = 1 ,771     ,42.7,45.4,48.3
BEGIN DESCRIPTION:
structure xs 2; 6.6 ft between structure and xs
END DESCRIPTION:
XS GIS Cut Line= 4
2246467.69305691516256.7470353972246093.74056117516372.053602124
2246036.21474874516525.2565465522246011.86954206516854.926211644
#Sta/Elev= 30
       0 3081.59    70.7 3053.67    86.3 3045.18   112.5 3036.56   141.8 3036.92
   162.7  3039.7   204.6 3036.38   310.3 3034.41   346.9 3031.45   418.3 3031.74
   426.7 3028.04   435.3 3026.24   449.3 3028.17   456.6 3031.97   520.6 3034.62
   554.9 3038.21     591 3037.35     595 3036.24     603 3030.06   607.2 3028.54
   643.1  3028.6   658.8 3036.85   663.2 3037.47   734.2  3039.8   775.5 3036.93
   823.6 3040.16   843.7 3039.87   851.7 3038.37   875.3 3043.04   885.5 3045.29
#Mann= 4 ,-1,0
       0     .06       0   426.7    .045       0   449.3     .06       0
   875.3      .1       0
#XS Ineff= 2 ,-1
       0   424.1 3030.45   451.5     550 3030.45
Permanent Ineff=
       F       F
Bank Sta=426.7,449.3
XS Rating Curve= 0 ,0
Exp/Cntr(USF)=0,0
Exp/Cntr=0.5,0.3

Type RM Length L Ch R = 1 ,725     ,119.8,115.6,112.2
BEGIN DESCRIPTION:
structure xs 1
END DESCRIPTION:
XS GIS Cut Line= 3
2246125.89235493516243.8060235452246011.51316715516437.842145668
2245936.96244654516699.280289161
#Sta/Elev= 30
       0 3040.89      62 3030.73      90 3029.44   151.2 3030.16   154.8 3029.84
  161.973026.286     178 3025.05   183.4 3026.29   187.3 3028.69   189.2 3029.09
   209.7 3029.06   219.8 3032.34   224.5 3032.69   228.7 3032.61   245.3 3028.13
   257.8 3030.62   270.3 3035.96   298.6 3038.07   311.6  3037.5   327.7 3033.54
   345.2 3031.35   353.6 3027.24   361.8 3026.31   370.1 3026.47   382.8 3029.13
   386.8 3030.39   395.1  3035.7   399.2  3036.7   424.2 3035.52   497.1  3034.8
#Mann= 3 ,-1,0
       0     .06       0  161.97    .045       0   183.4     .06       0
Bank Sta=161.97,183.4
XS Rating Curve= 0 ,0
Exp/Cntr(USF)=0,0
Exp/Cntr=0.3,0.1

Type RM Length L Ch R = 1 ,610     ,185.5,188.7,189.7
XS GIS Cut Line= 5
2246105.34043104516244.0660695962245937.41386077516330.321156556
2245907.82878264516435.3273493762245836.15788913516485.330298338
2245790.73854382516642.006205085
#Sta/Elev= 30
       0 3040.94    46.2 3033.25    81.9 3029.29   118.2 3026.88     177 3024.71
   195.9    3025   208.4 3026.62  215.69 3021.99   220.8 3020.57     225 3020.48
   229.2    3021   230.63022.019   237.5 3025.44   254.1 3025.59   262.4 3028.21
     279  3027.1   287.3 3027.61   307.2 3027.03   312.1 3025.84   321.8 3021.79
   326.7 3021.23   336.3 3021.54   344.9 3023.88   362.2 3025.51   418.4 3026.44
   443.4 3030.71   462.6 3031.27   480.9  3030.8   522.5 3033.25   548.4 3033.52
#Mann= 6 ,-1,0
       0     .06       0  215.69    .045       0   230.6     .06       0
  327.88     .07       0  455.27     .06       0  465.27     .03       0
Bank Sta=215.69,230.6
XS Rating Curve= 0 ,0
Exp/Cntr(USF)=0,0
Exp/Cntr=0.3,0.1

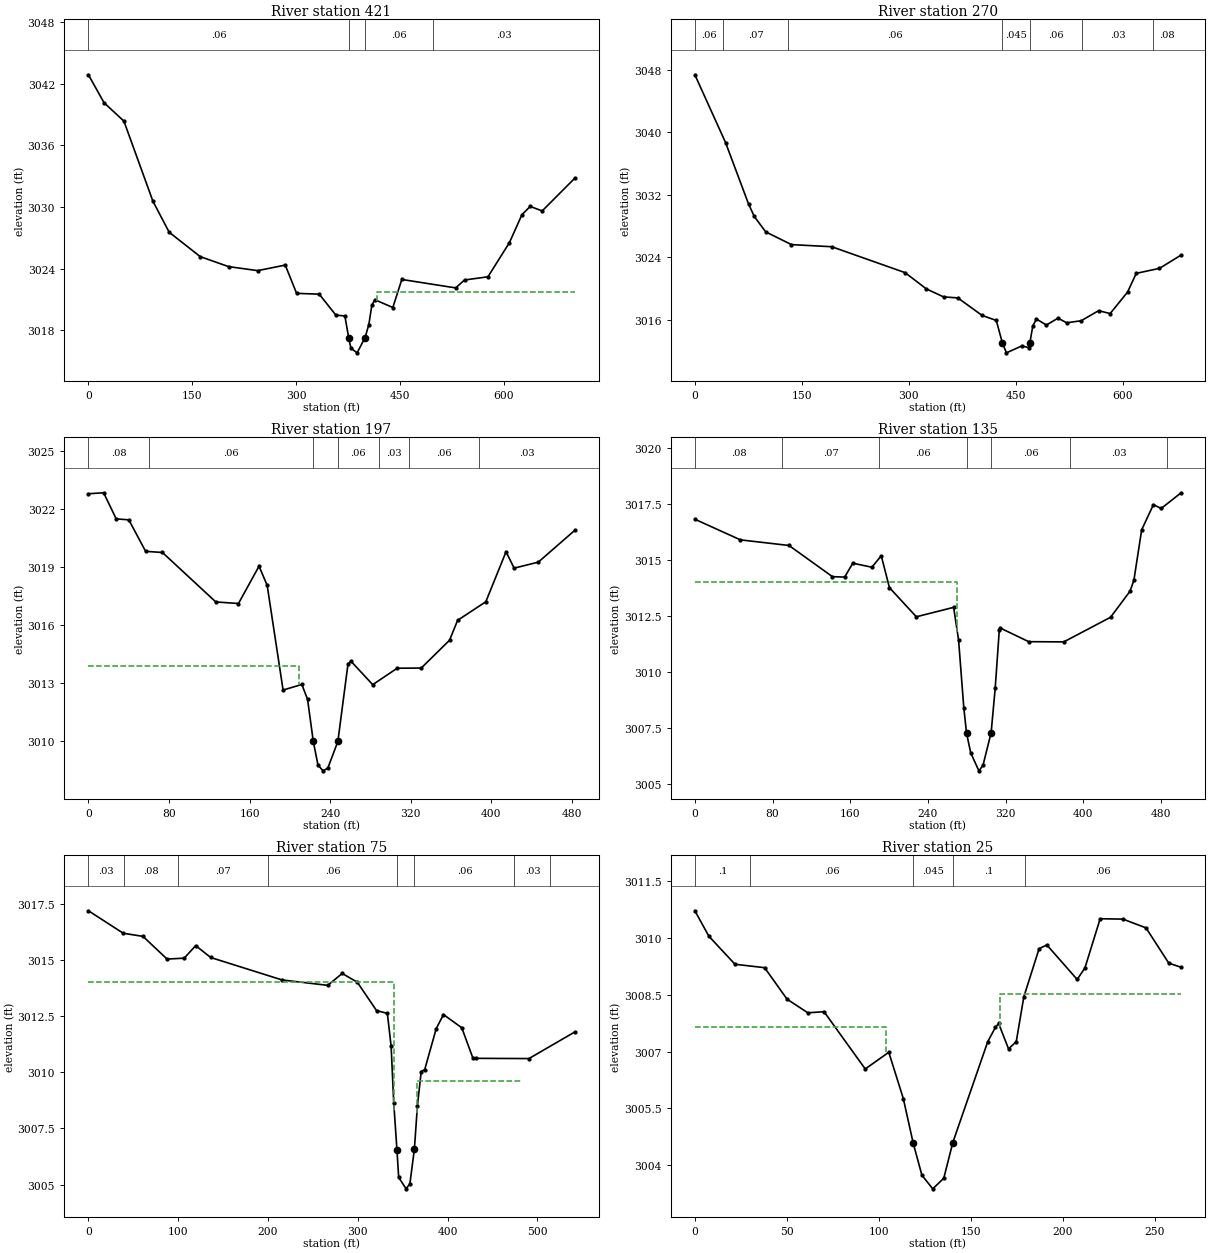
Type RM Length L Ch R = 1 ,421     ,143.5,150.7,166.4
XS GIS Cut Line= 4
2246098.29996735516236.6301809822245761.30869388516309.165559418
2245702.82574632516450.3417426212245779.76563152516640.649174097
#Sta/Elev= 30
       0 3042.88    22.6 3040.16    51.3 3038.37    93.2 3030.58   116.7 3027.56
   161.7 3025.18   202.7 3024.21   244.7 3023.82   284.5 3024.36   300.9 3021.61
   333.6 3021.53   357.7 3019.49   370.7 3019.41   376.2 3017.29   379.4 3016.27
   388.4 3015.82   399.9 3017.31   405.3 3018.57   409.7 3020.45     414 3020.99
     440 3020.23     453 3022.96   530.8 3022.14   543.7 3022.91   577.5 3023.22
   608.4 3026.53   626.7 3029.27   638.6 3030.07   655.9 3029.63   702.8  3032.8
#Mann= 4 ,-1,0
       0     .06       0   376.2    .045       0   399.9     .06       0
  497.52     .03       0
#XS Ineff= 2 , 0
                          417.35         3021.71
Permanent Ineff=
       F       F
Bank Sta=376.2,399.9
XS Rating Curve= 0 ,0
Exp/Cntr(USF)=0,0
Exp/Cntr=0.3,0.1

Type RM Length L Ch R = 1 ,270     ,72.4,73.3,74.9
XS GIS Cut Line= 4
2246042.95596503516207.6137715562245645.90826336516249.933480033
2245573.34587057516309.2298921532245607.41427602516495.076271442
#Sta/Elev= 30
       0 3047.39      43 3038.71    75.2 3030.86    83.2 3029.26    99.3 3027.27
   135.5 3025.64   191.9 3025.37   294.8 3022.05   324.6 3019.97   348.7 3018.95
   368.9 3018.81   402.8 3016.57   422.7 3015.93  431.133013.088   436.9 3011.78
   458.4 3012.66   468.2 3012.46  469.833013.075   473.9 3015.22     479 3016.11
     493 3015.34   509.2 3016.22   521.4 3015.63   541.8 3015.89   566.2 3017.18
   582.4 3016.81   606.8 3019.56     619 3021.96   651.6  3022.6   681.9  3024.3
#Mann= 7 ,-1,0
       0     .06       0      40     .07       0     130     .06       0
  431.13    .045       0  469.83     .06       0  543.01     .03       0
  643.01     .08       0
Bank Sta=431.13,469.83
XS Rating Curve= 0 ,0
Exp/Cntr(USF)=0,0
Exp/Cntr=0.3,0.1

Type RM Length L Ch R = 1 ,197     ,53.9,62.5,65.7
BEGIN DESCRIPTION:
structure xs 4
END DESCRIPTION:
XS GIS Cut Line= 4
 2245778.6698206516138.6180204992245612.20725267516187.637672403
 2245519.2741626516255.0396937732245529.87235732516449.207072801
#Sta/Elev= 30
       0 3022.79    15.1 3022.84    27.6 3021.49    40.1 3021.44    56.8 3019.81
    73.5 3019.75   126.5 3017.19     149 3017.11   169.4 3019.04   177.5 3018.05
   193.3 3012.63   211.9 3012.92   217.6 3012.15   223.3 3009.97   227.9 3008.76
   232.9 3008.45   237.7 3008.59   247.7 3009.97   257.7 3013.96   260.6 3014.13
   282.3 3012.91   306.6 3013.76   330.5 3013.77   358.6 3015.21   366.6 3016.24
   394.6  3017.2   414.7 3019.79   422.7 3018.94   446.7 3019.25   482.8 3020.89
#Mann= 7 ,-1,0
       0     .08       0      60     .06       0   223.3    .045       0
   247.7     .06       0  288.33     .03       0  318.33     .06       0
  388.33     .03       0
#XS Ineff= 2 , 0
           209.3 3013.85
Permanent Ineff=
       F       F
Bank Sta=223.3,247.7
XS Rating Curve= 0 ,0
Exp/Cntr(USF)=0,0
Exp/Cntr=0.5,0.3

Type RM Length L Ch R = 1 ,135     ,60.9,60,58.1
BEGIN DESCRIPTION:
structure xs 3; 9.4 ft between structure and xs
END DESCRIPTION:
XS GIS Cut Line= 3
2245795.52032594  516099.30017472245483.86206673516195.759256433
2245470.80122998516369.597742368
#Sta/Elev= 30
       0 3016.81    46.9 3015.89    96.9 3015.64   141.6 3014.25   154.2 3014.23
   162.6 3014.85   182.2 3014.67   191.9 3015.18   200.3 3013.76     228 3012.46
   266.4 3012.88   271.5 3011.42   276.9 3008.39279.69973007.271     284 3006.39
   292.4 3005.59   296.6 3005.83     305 3007.29   309.2 3009.27   313.4 3011.86
   314.3 3011.96   343.7 3011.35   379.8 3011.34     428 3012.44     448  3013.6
     452 3014.09     460 3016.34   472.1 3017.46   480.1 3017.29   500.6 3017.99
#Mann= 7 ,-1,0
       0     .08       0      90     .07       0     190     .06       0
279.6997    .045       0     305     .06       0  386.24     .03       0
  486.24     .06       0
#XS Ineff= 2 ,-1
       0   270.3 3014.01   314.4   432.5 3011.69
Permanent Ineff=
       F       F
Bank Sta=279.6997,305
XS Rating Curve= 0 ,0
Exp/Cntr(USF)=0,0
Exp/Cntr=0.5,0.3

Type RM Length L Ch R = 1 ,75      ,49.5,49.5,49.5
BEGIN DESCRIPTION:
structure xs 2; 9.1 ft between structure and xs
END DESCRIPTION:
XS GIS Cut Line= 3
 2245806.2433748516045.6849304292245448.48447831516156.575516004
2245417.16760142516320.641379668
#Sta/Elev= 30
       0 3017.19    38.8 3016.19    60.8 3016.05    87.6 3015.04   106.7 3015.08
   119.5 3015.64   136.2 3015.11   215.7 3014.11   266.6 3013.87   282.7  3014.4
   299.5 3014.01   320.9 3012.75     333 3012.62   337.2 3011.15   340.1 3008.64
343.69943006.528   345.6 3005.32   353.9 3004.81   358.1 3005.04   363.1 3006.58
   366.5 3008.52   370.7 3010.03   374.6 3010.12   387.4 3011.94   395.5 3012.57
   415.9 3011.98   428.1 3010.65   432.2 3010.62   490.7 3010.61   541.6 3011.79
#Mann= 8 ,-1,0
       0     .03       0      40     .08       0     100     .07       0
     200     .06       0343.6994    .045       0   363.1     .06       0
  474.55     .03       0  514.55     .06       0
#XS Ineff= 2 ,-1
       0   340.7 3014.01   365.9   481.7  3009.6
Permanent Ineff=
       F       F
Bank Sta=343.6994,363.1
XS Rating Curve= 0 ,0
Exp/Cntr(USF)=0,0
Exp/Cntr=0.5,0.3

Type RM Length L Ch R = 1 ,25      ,,,
BEGIN DESCRIPTION:
structure xs 1
END DESCRIPTION:
XS GIS Cut Line= 3
2245520.29540535516038.5362311932245394.68254734516151.894176223
 2245369.7076756516243.659248067
#Sta/Elev= 30
       0 3010.71     7.6 3010.04    21.8  3009.3    37.9 3009.21    50.1 3008.38
    61.4 3008.02    70.2 3008.05    92.6 3006.54   105.4 3006.98   113.3 3005.76
   118.7 3004.58   123.4 3003.74   129.3 3003.38   135.3 3003.66   140.2  3004.6
   159.2 3007.26   163.4 3007.64   165.1 3007.74   170.5 3007.07   174.7 3007.26
   178.8 3008.44   187.1 3009.71   191.3 3009.81   207.8  3008.9     212  3009.2
   220.3  3010.5   232.7 3010.49   245.2 3010.26   257.6 3009.33   264.3 3009.22
#Mann= 5 ,-1,0
       0      .1       0      30     .06       0   118.7    .045       0
   140.2      .1       0   179.2     .06       0
#XS Ineff= 2 , 0
          104.11 3007.64  165.92         3008.51
Permanent Ineff=
       F       F
Bank Sta=118.7,140.2
XS Rating Curve= 0 ,0
Exp/Cntr(USF)=0,0
Exp/Cntr=0.3,0.1
LCMann Table=0

Chan Stop Cuts=-1
Use User Specified Reach Order=0
Composite Channel Slope=5